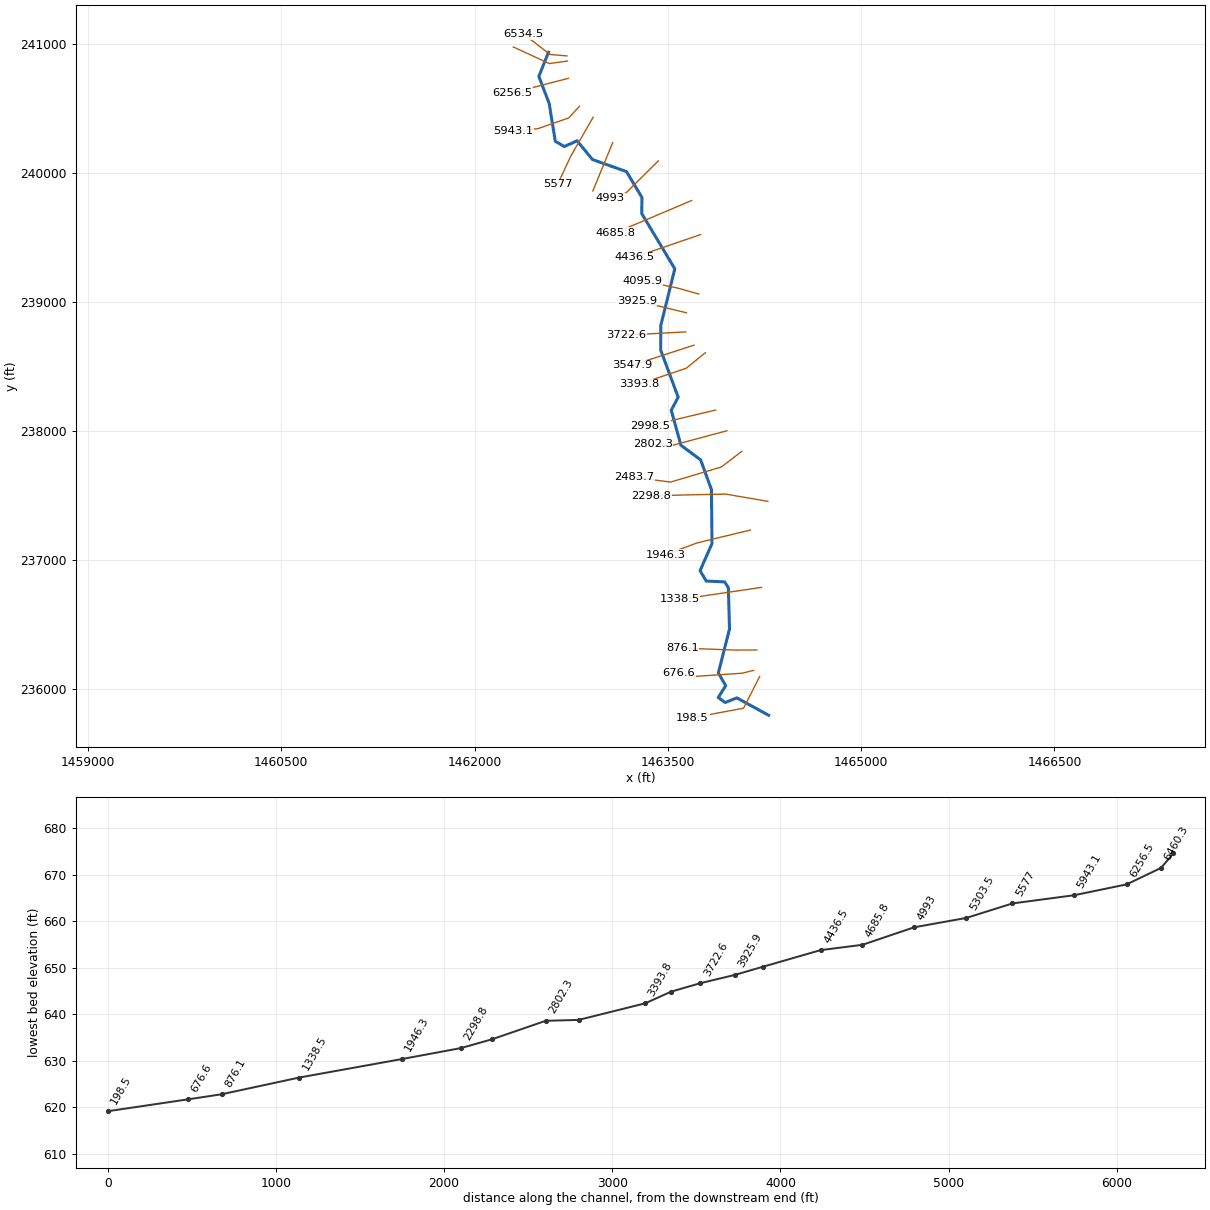
--- BFFLRN.prj (project) ---

Proj Title=BFFLRN
Current Plan=p01
Default Exp/Contr=0,0
English Units
Geom File=g01
Flow File=f01
Plan File=p01
BEGIN DESCRIPTION:
END DESCRIPTION:
DSS Export Rating Curves= 0
DSS Export Rating Curve Sorted= 0
DSS Export Volume Flow Curves= 0
DXF OffsetX= 0
DXF OffsetY= 0
DXF ScaleX= 0
DXF ScaleY= 0

--- BFFLRN.p01 (plan) ---

Plan Title=Floodplain
Program Version=4.00
Geom File=g01
Flow File=f01
K Sum by GR=0
Std Step Tol=0.01
Critical Tol=0.01
Num of Std Step Trials=20
Max Error Tol=0.3
Flow Tol Ratio=0.001
Split Flow NTrial=30
Split Flow Tol=0.02
Split Flow Ratio=0.02
Log Output Level=0
Friction Slope Method=1
Unsteady Friction Slope Method=2
Unsteady Bridges Friction Slope Method=1
Global Log Level=0
CheckData=False
Run HTab=0
Run UNet=0
Run PostProcess=0
UNET Theta=0
UNET Theta Warmup=0
UNET ZTol=0
UNET ZSATol=0
UNET MxIter=0
UNET MaxInSteps=0
UNET DtIC=0
UNET DtMin=0
UNET MaxCRTS=0
UNET WFStab=0
UNET SFStab=0
UNET WFX=0
UNET SFX=0
UNET DSS MLevel=0
UNET DZMax Abort=0
UNET Convert EG Bridges=0
UNET Use Existing IB Tables=0
UNET Froude Limit=0
UNET Froude Power=0
Write IC File=0
Echo Input=False
Echo Output=False
Write Detailed=0

--- BFFLRN.f01 (steady flow) ---

Flow Title=NFF Regression Equation
Program Version=4.10
Number of Profiles= 1
Profile Names=P100yr
River Rch & RM=BFFLRN,Main            ,6534.5
769.4237
River Rch & RM=BFFLRN,Main            ,6256.5
928.0648
River Rch & RM=BFFLRN,Main            ,5943.1
    1046
River Rch & RM=BFFLRN,Main            ,5577
1049.919
River Rch & RM=BFFLRN,Main            ,876.1
1166.047
River Rch & RM=BFFLRN,Main            ,198.5
1170.618
Boundary for River Rch & Prof#=BFFLRN,Main            , 1
Up Type= 0
Dn Type= 3
Dn Slope=0.006
DSS Import GetInterval= 0
DSS Import GetPeak= 0
DSS Import FillOption= 0

--- BFFLRN.g01 (geometry) ---

Geom Title=USGS 10m DEM
Program Version=4.10

River Reach=BFFLRN          ,Main
Reach XY= 30
     1462573.817      240937.396     1462498.817      240750.793
     1462579.459      240539.074     1462626.334      240247.147
     1462696.647      240206.001     1462795.773      240250.888
     1462915.079      240105.311     1463178.938       240011.73
     1463299.179       239810.48     1463297.162      239686.305
     1463553.952      239257.389     1463445.407      238819.655
     1463444.027      238627.679     1463580.106      238261.495
     1463526.251      238159.721     1463601.508      237888.287
     1463753.996      237775.109     1463838.125      237544.554
     1463842.526      237125.651     1463749.894      236915.146
     1463797.526      236834.751     1463941.073      236827.999
     1463969.376      236782.613     1463978.455      236462.917
     1463891.645      236121.363     1463948.819       236023.13
     1463890.709      235930.344     1463945.396       235892.15
      1464035.24      235928.174     1464281.585       235793.25

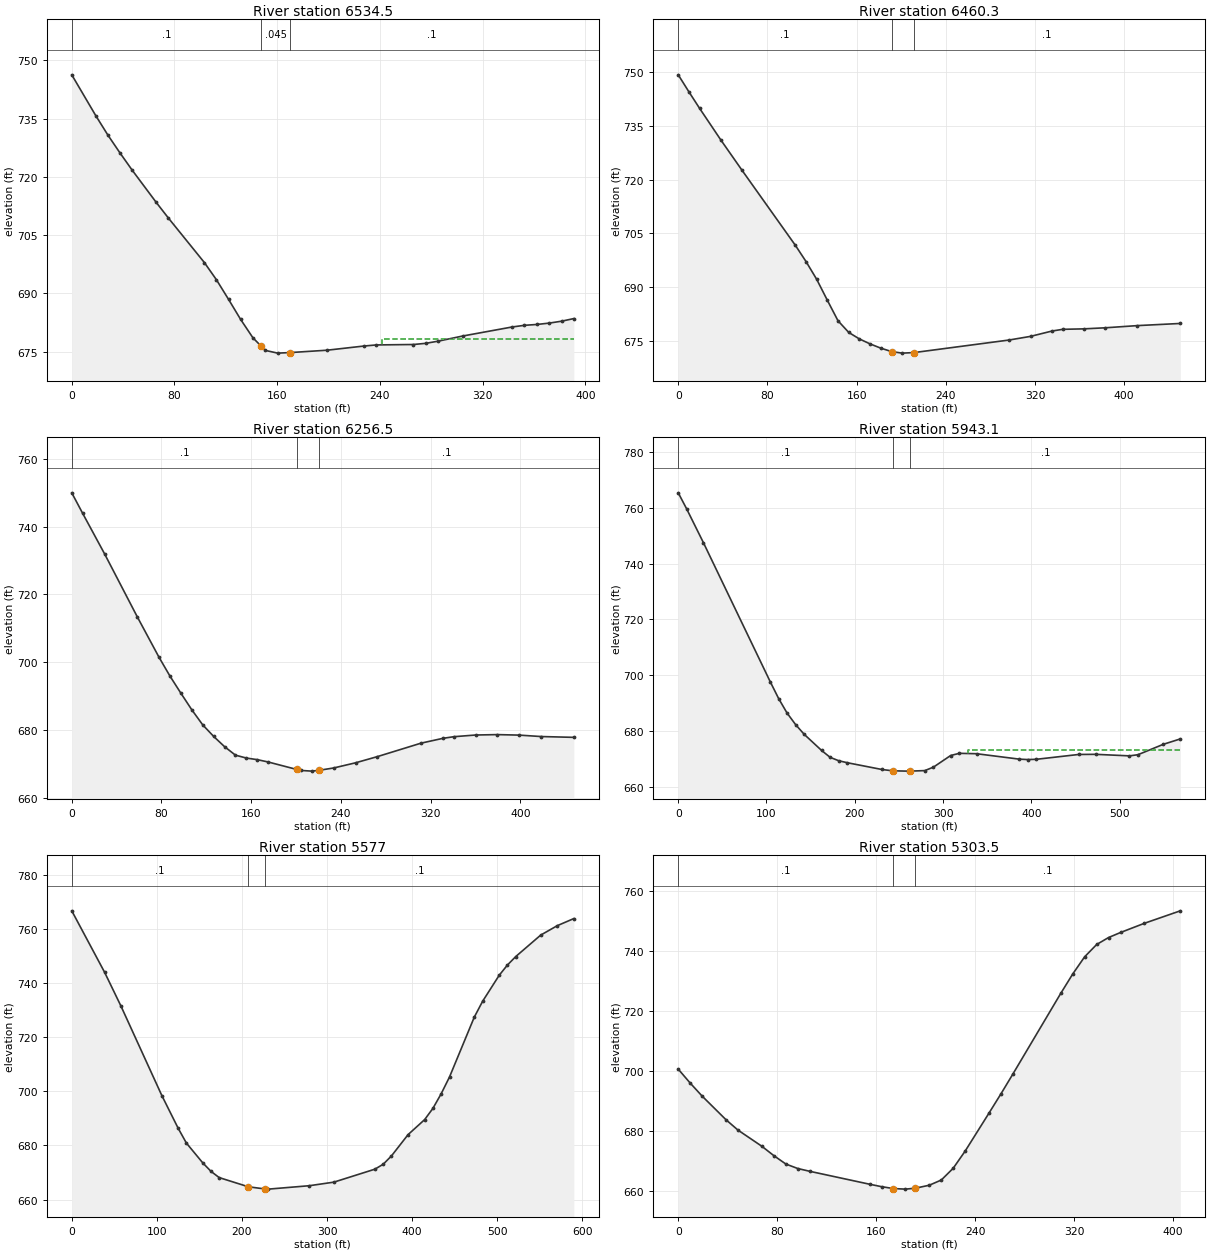
Type RM Length L Ch R = 1 ,6534.5  ,71.9,74.3,79.9
XS GIS Cut Line= 3
     1462717.046      240909.647      1462585.97      240920.469
     1462380.674      241079.323
#Sta/Elev= 29
       0  746.26    18.8  735.69    28.2  730.71    37.6  726.13      47  721.74
    65.8  713.41    75.2  709.41   103.3  697.92   112.7  693.49   122.1  688.46
   131.5   683.3   141.1  678.55  147.66676.3522   150.8   675.3   160.4   674.6
     170  674.74   198.8  675.35   227.7  676.43   237.3  676.71   266.1  676.82
   275.7  677.12   285.4  677.68   304.6  679.01     343  681.33   352.6  681.76
   362.3  681.98   371.9  682.33   381.5  682.82   391.1   683.5
#Mann= 3 , 0 , 0
       0      .1       0  147.66    .045       0     170      .1       0
#XS Ineff= 2 , 0
                          241.42          678.24
Permanent Ineff=
       F       F
Bank Sta=147.66,170
XS Rating Curve= 0 ,0
Exp/Cntr=0.3,0.1

Type RM Length L Ch R = 1 ,6460.3  ,187,203.8,220.6
XS GIS Cut Line= 3
     1462721.516      240869.591     1462579.589      240850.059
     1462300.944      240978.966
#Sta/Elev= 25
       0  749.33     9.6  744.56    19.1  739.98    38.2  731.11    57.3  722.59
   105.1  701.61   114.6   697.1   124.2  692.11   133.7  686.28   143.3  680.52
   152.9  677.27   162.4  675.45     172  674.06   181.6  672.87   191.4671.9011
   200.8  671.47   211.4671.6196   296.8  675.14     316  676.16   335.2  677.65
   344.8  678.13   363.9  678.26   383.1  678.56   411.9  679.17   450.3  679.77
#Mann= 3 , 0 , 0
       0      .1       0   191.4    .045       0   211.4      .1       0
Bank Sta=191.4,211.4
XS Rating Curve= 0 ,0
Exp/Cntr=0.3,0.1

Type RM Length L Ch R = 1 ,6256.5  ,310.9,313.3,315
XS GIS Cut Line= 2
     1462728.027      240735.476     1462294.433      240623.497
#Sta/Elev= 30
       0  749.94     9.7   743.9    29.2     732    58.4  713.42    77.9  701.44
    87.6  695.93    97.4  690.86   107.1  685.99   116.8  681.57   126.6  678.15
   136.3  675.14     146  672.64   155.8  671.79   165.5  671.32   175.2  670.63
   200.8668.4219   204.4  668.14   214.2  667.94   220.8668.1982   233.6  668.87
   253.1  670.39   272.6  672.22   311.5  676.18     331   677.6   340.7  678.08
   360.2  678.58   379.7   678.7   399.1  678.55   418.6  678.13   447.8  677.89
#Mann= 3 , 0 , 0
       0      .1       0   200.8    .045       0   220.8      .1       0
Bank Sta=200.8,220.8
XS Rating Curve= 0 ,0
Exp/Cntr=0.3,0.1

Type RM Length L Ch R = 1 ,5943.1  ,344.1,366.1,385.2
XS GIS Cut Line= 4
     1462814.138      240518.957     1462730.631      240428.184
     1462491.048      240344.851     1462300.249      240324.513
#Sta/Elev= 30
       0  765.34     9.5  759.61    28.5   747.5   104.4  697.53   113.8  691.59
   123.3  686.42   133.1  682.23   142.8  678.77   162.4  673.02   172.1  670.54
   181.9  669.32   191.6  668.61   230.7  666.19   242.9 665.715   259.9   665.6
   262.9   665.6   279.4  665.79   289.2  667.04   308.7   671.2   318.5  671.98
     338  671.84   386.6  669.89   396.2  669.74   405.8  669.84   453.8  671.57
   472.9  671.62   511.3  671.07   520.9  671.48   549.7  675.22   568.9  677.14
#Mann= 3 , 0 , 0
       0      .1       0   242.9    .045       0   262.9      .1       0
#XS Ineff= 2 , 0
                          328.43          673.06
Permanent Ineff=
       F       F
Bank Sta=242.9,262.9
XS Rating Curve= 0 ,0
Exp/Cntr=0.3,0.1

Type RM Length L Ch R = 1 ,5577    ,269.8,273.5,276.2
XS GIS Cut Line= 3
     1462919.751      240432.803     1462747.008      240132.455
      1462643.71      239911.969
#Sta/Elev= 30
       0  766.68    38.5  744.02    57.8  731.49   105.9  698.38   125.1  686.29
   134.7  680.86     154  673.52   163.6  670.41   173.2  668.11   207.6   664.7
   227.6663.8803     231  663.84   279.1   665.1     308  666.42   356.2  671.21
     366  673.04   375.7  676.12   395.2  683.98   414.7  689.54   424.4  693.69
   434.1  699.08   443.9  705.29   473.1  727.46   482.8  733.26   502.3  742.87
     512  746.67   521.8   749.8     551   757.7   570.5  761.19     590  763.82
#Mann= 3 , 0 , 0
       0      .1       0   207.6    .045       0   227.6      .1       0
Bank Sta=207.6,227.6
XS Rating Curve= 0 ,0
Exp/Cntr=0.3,0.1

Type RM Length L Ch R = 1 ,5303.5  ,320.3,310.5,300.3
XS GIS Cut Line= 2
     1463072.168      240237.273     1462918.088      239861.839
#Sta/Elev= 30
       0  700.72     9.7  696.06    19.3  691.74    38.6  683.86    48.3   680.4
    67.6  675.01    77.3  671.88      87  669.09    96.6   667.6   106.3  666.67
   154.6  662.37   164.3  661.55   173.9  660.92   183.6  660.73   191.5661.0253
   202.9  662.03   212.6  663.76   222.2  667.67   231.9  673.41   251.2  686.09
   260.9  692.53   270.6  699.17   309.2  725.99   318.9  732.46   328.5  738.17
   338.2  742.26   347.8  744.58   357.5  746.26   376.8  749.33   405.8  753.48
#Mann= 3 , 0 , 0
       0      .1       0   173.9    .045       0   191.5      .1       0
Bank Sta=173.9,191.5
XS Rating Curve= 0 ,0
Exp/Cntr=0.3,0.1

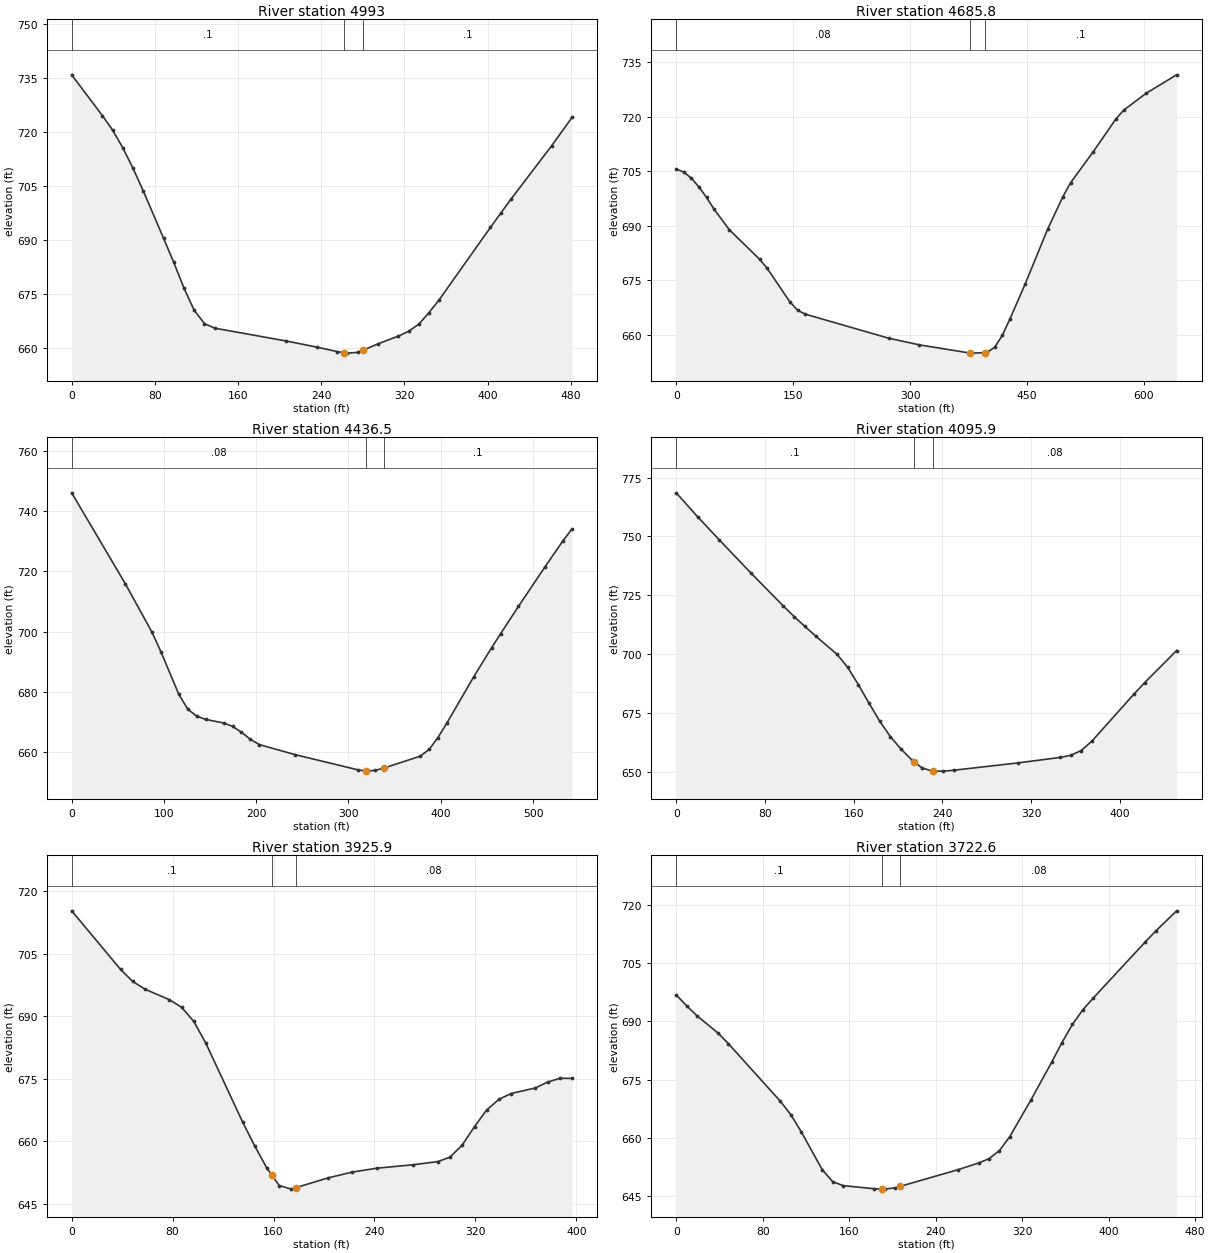
Type RM Length L Ch R = 1 ,4993    ,315.8,307.2,297.1
XS GIS Cut Line= 3
     1463425.944      240094.851     1463174.641      239846.153
       1463054.3      239803.462
#Sta/Elev= 30
       0  735.84    29.5  724.54    39.3  720.54    49.1  715.65    58.9  709.98
    68.8   703.7    88.4  690.52    98.2  683.83     108  676.74   117.8  670.58
   127.7  666.92   137.5  665.63   206.2  662.08   235.7  660.38   255.4  659.13
  261.54658.8693   265.2  658.71     275  658.91   280.2659.5123   294.6  661.28
   314.3  663.44   324.1  664.77   333.9  666.76   343.7  669.96   353.6  673.57
   402.7  693.53   412.5  697.45   422.3  701.31   461.6  716.19   481.2  724.03
#Mann= 3 , 0 , 0
       0      .1       0  261.54    .045       0   280.2      .1       0
Bank Sta=261.54,280.2
XS Rating Curve= 0 ,0
Exp/Cntr=0.3,0.1

Type RM Length L Ch R = 1 ,4685.8  ,251.2,249.2,247.2
XS GIS Cut Line= 2
     1463685.058      239787.559     1463093.912      239537.559
#Sta/Elev= 30
       0  705.65     9.7   704.8    19.4  703.12    29.2  700.68    38.9  697.81
    48.6  694.56    68.1  688.92     107  680.78   116.7  678.29   145.9  669.01
   155.6  666.78   165.3  665.69   272.3  659.07   311.2  657.25   376.2654.9899
   379.3  654.95   396.2  655.09   398.7  655.14   408.4  656.57   418.2  659.84
   427.9  664.31   447.3  673.86   476.5  689.15     496  698.06   505.7  701.84
   534.9  710.42     564  719.46   573.8  721.84   602.9  726.53   641.8  731.59
#Mann= 3 , 0 , 0
       0     .08       0   376.2    .045       0   396.2      .1       0
Bank Sta=376.2,396.2
XS Rating Curve= 0 ,0
Exp/Cntr=0.3,0.1

Type RM Length L Ch R = 1 ,4436.5  ,353,340.6,327
XS GIS Cut Line= 2
     1463754.069      239523.237     1463241.048      239347.455
#Sta/Elev= 30
       0  746.07    58.1  715.95    87.2  699.77    96.8  693.31   116.2  679.21
   125.9  674.33   135.6     672   145.3  670.94   164.6  669.78   174.3  668.67
     184   666.7   193.7  664.33   203.4  662.59   242.1  659.27   309.9  654.26
   318.6653.8474   319.6   653.8   329.2  654.07   338.6654.8353   377.7  658.75
   387.4  660.99     397  664.94   406.7  669.78   435.8  685.09   455.1   694.7
   464.8  699.34   484.2   708.4   513.2  721.63   532.6  730.23   542.3  734.11
#Mann= 3 , 0 , 0
       0     .08       0   318.6    .045       0   338.6      .1       0
Bank Sta=318.6,338.6
XS Rating Curve= 0 ,0
Exp/Cntr=0.3,0.1

Type RM Length L Ch R = 1 ,4095.9  ,171.1,170.1,169
XS GIS Cut Line= 3
     1463739.196      239062.143     1463571.661      239109.018
      1463299.96      239164.573
#Sta/Elev= 30
       0   768.5    19.3  758.31    38.7  748.57    67.6  734.31    96.6   720.4
   106.3  715.95     116  711.76   125.6   707.7     145  699.88   154.6  694.37
   164.3  686.95     174     679   183.5  671.48   193.1  664.92   202.7  659.65
   212.2   655.1   214.5654.2519   221.8  651.56   231.4  650.25  231.95  650.25
   240.9  650.25   250.5  650.64   307.8  653.72   346.1  656.06   355.7  656.95
   365.2     659   374.8  662.94     413  683.07   422.6   687.9   451.3  701.49
#Mann= 3 , 0 , 0
       0      .1       0   214.5    .045       0  231.95     .08       0
Bank Sta=214.5,231.95
XS Rating Curve= 0 ,0
Exp/Cntr=0.3,0.1

Type RM Length L Ch R = 1 ,3925.9  ,195.8,203.3,210.4
XS GIS Cut Line= 2
     1463643.391      238916.466     1463257.975      239010.216
#Sta/Elev= 30
       0  715.26    38.7  701.21    48.4   698.3      58  696.47    77.4  693.93
    87.1  692.11    96.8  688.72   106.4  683.45   135.4  664.63   145.1  658.81
   154.8  653.46   158.4651.9256   164.5  649.33   174.1  648.46  177.63648.7986
   203.2  651.16   222.5  652.56   241.9  653.48   270.9  654.32   290.2  655.07
   299.9  656.14   309.6  659.06   319.3  663.48   328.9  667.45   338.6     670
   348.3  671.41   367.6  672.75   377.3  674.16     387  675.06   396.6  675.04
#Mann= 3 , 0 , 0
       0      .1       0   158.4    .045       0  177.63     .08       0
Bank Sta=158.4,177.63
XS Rating Curve= 0 ,0
Exp/Cntr=0.3,0.1

Type RM Length L Ch R = 1 ,3722.6  ,168.3,174.7,181.3
XS GIS Cut Line= 2
     1463638.574      238768.089     1463176.334      238743.132
#Sta/Elev= 30
       0  696.84     9.6  694.04    19.3  691.43    38.6  687.01    48.2  684.27
    96.4  669.36   106.1  665.89   115.7  661.48     135  651.74   144.7  648.64
   154.3  647.61   183.2   646.8  190.02646.7278   192.9   646.7   202.5  647.04
   207.3647.4227   260.4   651.7   279.7  653.44   289.3  654.56     299  656.66
   308.6  660.28   327.9  669.61   347.2  679.41   356.8  684.52   366.5  689.23
   376.1  692.99   385.8  696.05     434  710.55   443.6  713.34   462.9  718.56
#Mann= 3 , 0 , 0
       0      .1       0  190.02    .045       0   207.3     .08       0
Bank Sta=190.02,207.3
XS Rating Curve= 0 ,0
Exp/Cntr=0.3,0.1

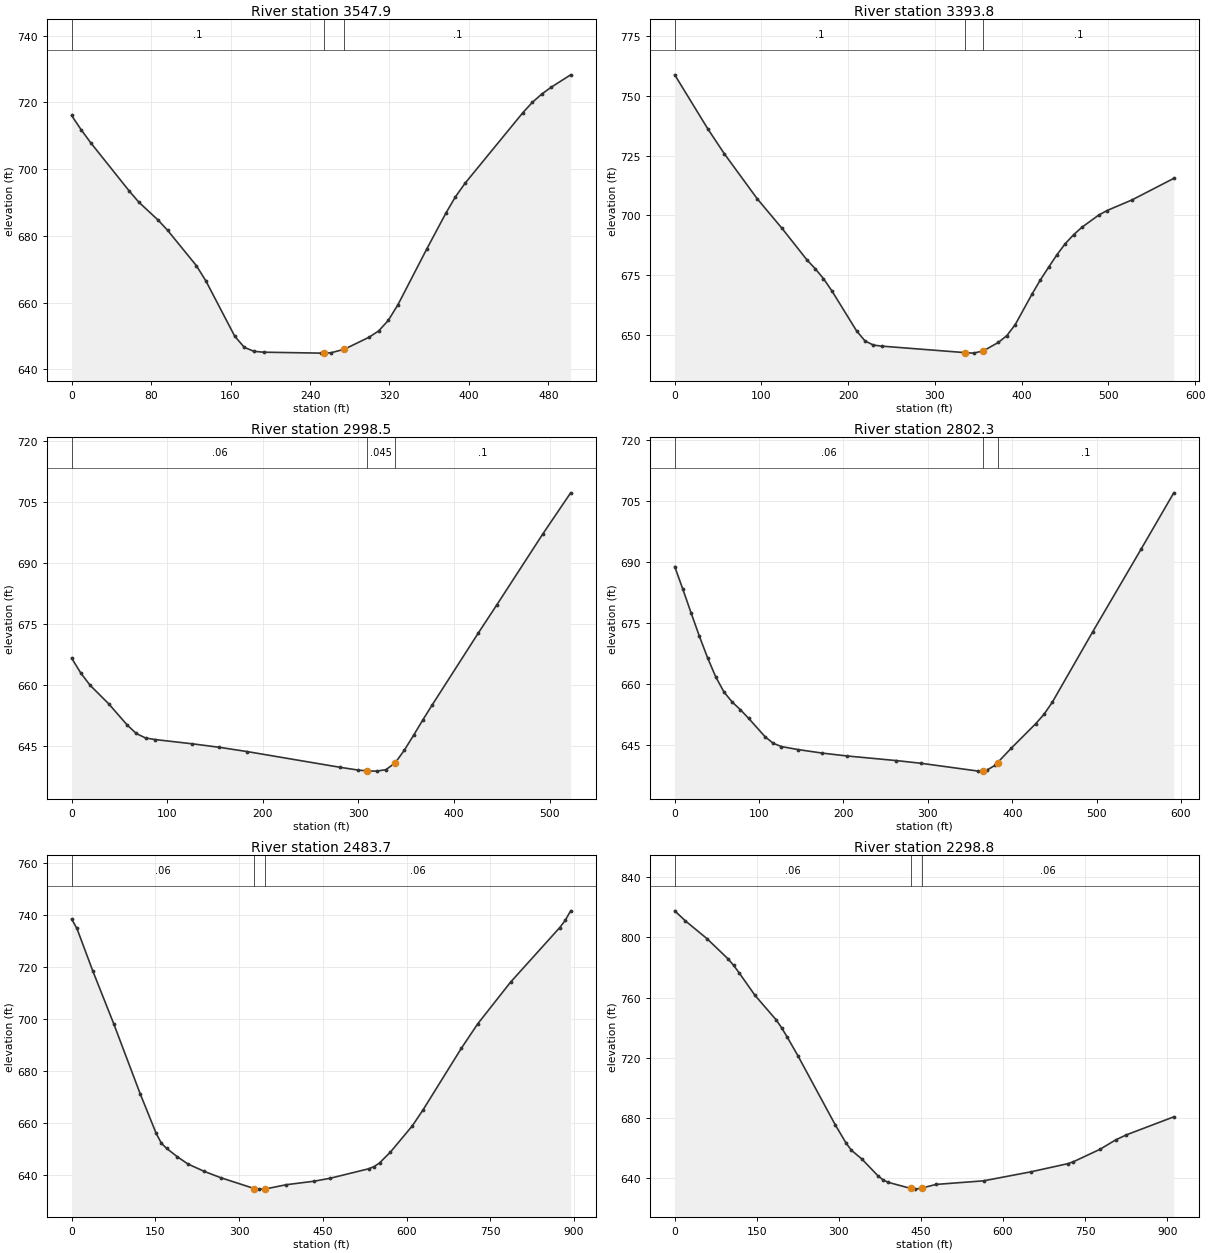
Type RM Length L Ch R = 1 ,3547.9  ,153.6,154.1,154.2
XS GIS Cut Line= 2
     1463703.287      238665.164     1463225.423      238510.216
#Sta/Elev= 30
       0  716.07     9.7  711.74    19.3  707.87      58  693.44    67.6  690.12
      87  684.75    96.6  681.68   125.6  671.08   135.2  666.49   164.2  649.95
   173.9  646.59   183.6  645.41   193.2  645.15   251.2  644.87   254.5644.8984
   260.8  644.96   274.5646.0257   299.5  649.64   309.1  651.52   318.8  654.67
   328.5  659.36   357.4  675.99   376.8  686.81   386.4   691.7   396.1  695.76
     454   716.8   463.7  719.96   473.4   722.5     483  724.56   502.4  728.24
#Mann= 3 , 0 , 0
       0      .1       0   254.5    .045       0   274.5      .1       0
Bank Sta=254.5,274.5
XS Rating Curve= 0 ,0
Exp/Cntr=0.3,0.1

Type RM Length L Ch R = 1 ,3393.8  ,397,395.3,392.4
XS GIS Cut Line= 3
     1463790.484      238606.414     1463642.914      238485.971
     1463278.267      238362.634
#Sta/Elev= 30
       0   758.8    38.1  736.22    57.1  725.83    95.2   706.9   123.8  694.53
   152.4  681.39   161.9  677.72   171.4  673.58     181  668.52   209.7  651.66
   219.4  647.46     229  645.73   238.6  645.29   334.8  642.57   344.5  642.36
     356643.3265   373.3  646.87     383  649.71   392.6   654.3   411.8  666.95
   421.4  672.89   431.1   678.3   440.7  683.52   450.3  688.17   459.9   691.9
   469.6  695.05   488.8   700.1   498.4  702.01   527.3  706.47   575.4  715.48
#Mann= 3 , 0 , 0
       0      .1       0   334.8    .045       0     356      .1       0
Bank Sta=334.8,356
XS Rating Curve= 0 ,0
Exp/Cntr=0.3,0.1

Type RM Length L Ch R = 1 ,2998.5  ,195.7,196.3,196.3
XS GIS Cut Line= 2
     1463870.779      238161.535     1463362.966      238041.092
#Sta/Elev= 25
       0  666.62     9.7   662.9    19.3  659.94    38.7  655.39      58  650.18
    67.6  648.06    77.3  646.96      87  646.58   125.6  645.54   154.6  644.66
   183.6  643.61   280.3  639.76   299.6  639.06   309.3  638.85   318.9   638.8
   328.6  639.15   338.3   640.8   347.9  643.93   357.6  647.61   367.3   651.4
   376.9  655.02   425.2  672.74   444.6  679.68   492.9   697.2   521.9  707.28
#Mann= 3 , 0 , 0
       0     .06       0   309.3    .045       0   338.3      .1       0
Bank Sta=309.3,338.3
XS Rating Curve= 0 ,0
Exp/Cntr=0.3,0.1

Type RM Length L Ch R = 1 ,2802.3  ,317.9,318.6,319.2
XS GIS Cut Line= 3
     1463958.669      238000.945     1463517.046      237882.672
     1463383.582      237896.778
#Sta/Elev= 30
       0  688.81     9.7  683.22    19.4  677.44    29.2  671.73    38.9  666.45
    48.6  661.74    58.4  658.02    68.1  655.57    77.8  653.68    87.6  651.56
     107  647.06   116.7  645.44   126.5  644.63   145.9   643.9   175.1  643.02
   204.3  642.32   262.6  641.19   291.8  640.53   359.9   638.6  365.17638.7116
   369.6  638.81   379.4     640   382.6640.6973   398.8  644.23     428  650.29
   437.7  652.57   447.5  655.54   495.5  672.87     553  693.22   591.4  706.93
#Mann= 3 , 0 , 0
       0     .06       0  365.17    .045       0   382.6      .1       0
Bank Sta=365.17,382.6
XS Rating Curve= 0 ,0
Exp/Cntr=0.3,0.1

Type RM Length L Ch R = 1 ,2483.7  ,191.6,184.9,178
XS GIS Cut Line= 4
     1464073.079      237840.945     1463915.527      237719.851
     1463520.996      237602.664     1463239.746      237639.122
#Sta/Elev= 30
       0  738.44     9.5  734.84    37.8  718.57    75.7  698.06     123  671.19
   151.4   656.1   160.9  652.24   170.3  650.28   189.2   647.1   208.5  644.27
   237.9  641.42   267.3  639.01     327634.8661   335.9  634.63   345.7  634.64
   384.9  636.34   433.9  637.66   463.3  638.82   531.9  642.44   541.7  643.28
   551.5  644.69   571.1  648.88   610.3  658.96   629.8   665.2   698.3  688.84
   727.6  698.22   786.3   714.2   874.3  735.16   884.1  737.91   893.9  741.61
#Mann= 3 , 0 , 0
       0     .06       0     327    .045       0   345.7     .06       0
Bank Sta=327,345.7
XS Rating Curve= 0 ,0
Exp/Cntr=0.3,0.1

Type RM Length L Ch R = 1 ,2298.8  ,346.9,352.5,357.7
XS GIS Cut Line= 4
     1464276.595      237452.985     1463948.904      237509.408
     1463639.659      237502.898     1463369.477      237495.303
#Sta/Elev= 30
       0  817.67    19.6  810.95    58.7  799.26    97.8  785.62   107.6  781.46
   117.4  776.64   146.7   761.5   185.8  745.05   195.6  739.79   205.4   733.9
   224.9  721.53   293.4  675.46     313  663.47   322.7  658.64   342.2   652.7
   371.2  641.68   380.8  638.85   390.5  637.23   431.6 633.173   438.8  632.74
   451.6633.4347   477.5  635.86   564.5  638.26   651.5  644.28     719   649.7
   728.7  650.95     777  659.16   805.9  665.44   825.2  668.76   912.1  680.77
#Mann= 3 , 0 , 0
       0     .06       0   431.6    .045       0   451.6     .06       0
Bank Sta=431.6,451.6
XS Rating Curve= 0 ,0
Exp/Cntr=0.3,0.1

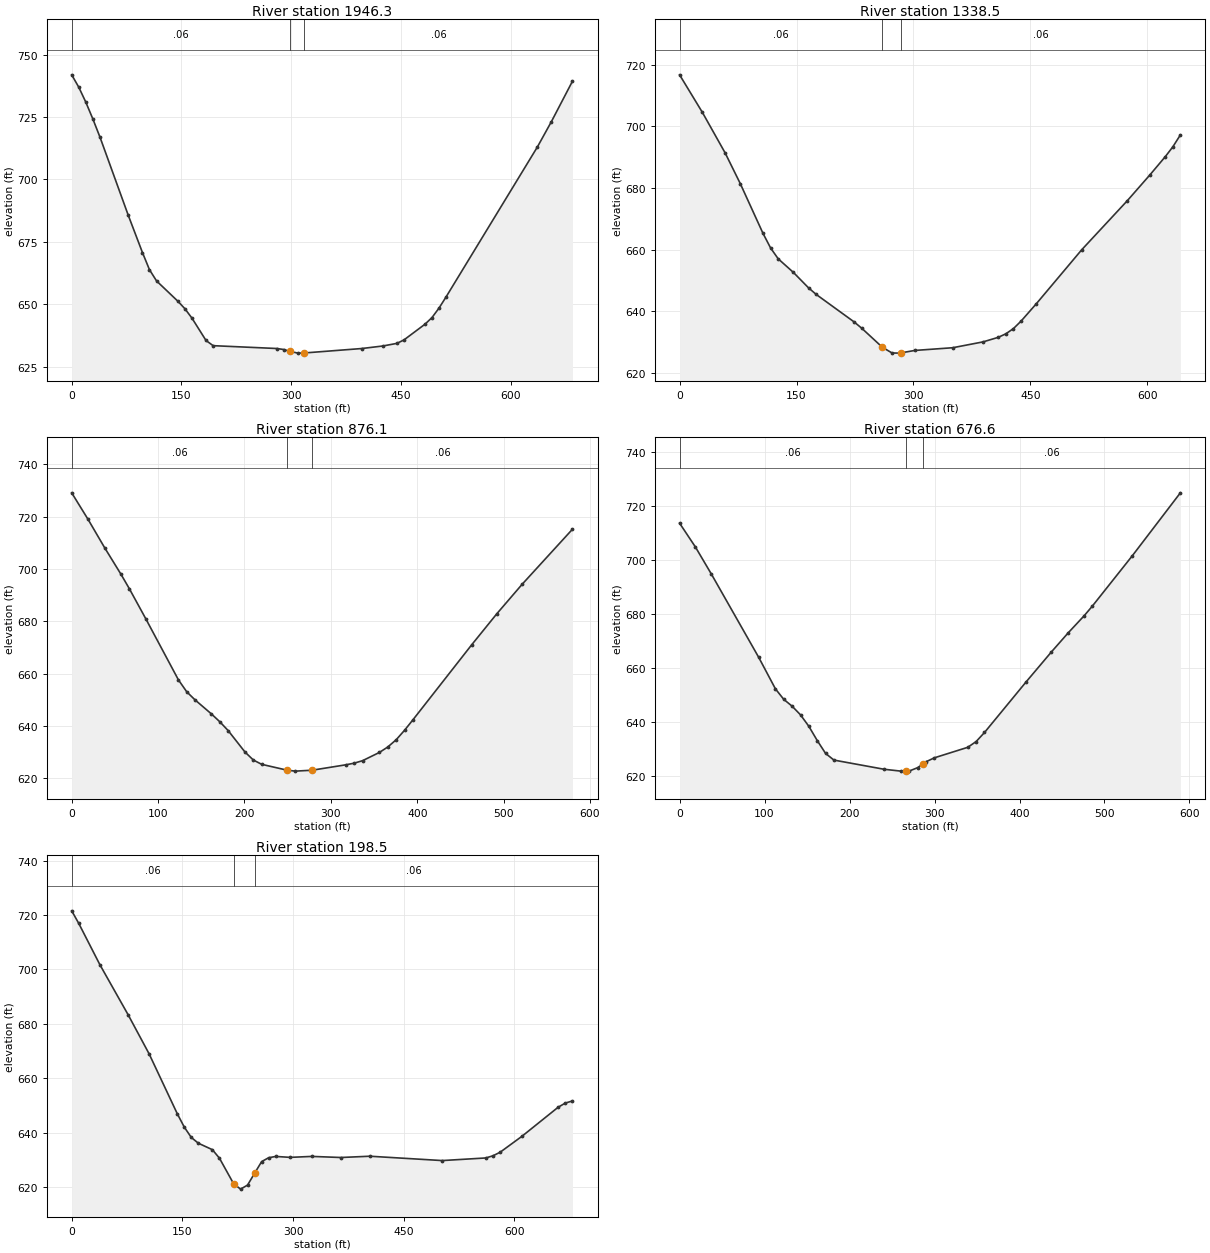
Type RM Length L Ch R = 1 ,1946.3  ,610.7,607.8,602.9
XS GIS Cut Line= 3
     1464140.961      237230.546     1463727.549      237130.719
     1463484.494      237040.658
#Sta/Elev= 30
       0  741.87     9.7  736.89    19.3  730.91      29  724.12    38.7  716.86
    77.3   685.6    96.7  670.67   106.3  663.79     116  659.29     145   651.2
   154.6   648.2   164.3  644.42   183.6  635.43   193.3  633.36   280.3  632.22
     290  631.81   297.8631.1031   309.3  630.37   317.8630.4302   396.3  632.21
   425.3  633.23   444.5  634.28   454.1  635.65   482.9  641.96   492.5  644.64
   502.1  648.44   511.7  652.89   636.5  712.96   655.7  723.14   684.5  739.34
#Mann= 3 , 0 , 0
       0     .06       0   297.8    .045       0   317.8     .06       0
Bank Sta=297.8,317.8
XS Rating Curve= 0 ,0
Exp/Cntr=0.3,0.1

Type RM Length L Ch R = 1 ,1338.5  ,466.4,462.4,457
XS GIS Cut Line= 2
     1464226.898      236785.667     1463591.482      236691.917
#Sta/Elev= 30
       0  716.66    29.2   704.5    58.4  691.35    77.8  681.41     107  665.24
   116.8  660.48   126.5  656.99     146  652.58   165.4  647.58   175.2  645.45
   223.8  636.54   233.6  634.49   260.1628.3043   272.5  626.46   282.2  626.41
  283.84 626.492   301.7  627.28   350.3  628.16   389.3  630.06   408.7  631.53
   418.5  632.68   428.2  634.37   437.9  636.77   457.4  642.38   515.8  659.94
   574.2  675.83   603.4  684.26   622.8  690.08   632.6   693.3   642.3  697.17
#Mann= 3 , 0 , 0
       0     .06       0   260.1    .045       0  283.84     .06       0
Bank Sta=260.1,283.84
XS Rating Curve= 0 ,0
Exp/Cntr=0.3,0.1

Type RM Length L Ch R = 1 ,876.1   ,197,199.5,202.4
XS GIS Cut Line= 3
     1464190.657       236299.99     1464028.982      236298.905
      1463611.23      236314.096
#Sta/Elev= 30
       0  729.13      19  718.95      38  708.23    57.1  697.98    66.6  692.57
    85.6  681.11   123.6  657.64   133.2   653.1   142.7  650.05   161.7  644.67
   171.4  641.68   181.1   638.3   200.6   630.1   210.3  627.04     220   625.4
   249.2  623.18   258.9  622.81   278.3  623.16   317.2  625.22     327  625.85
   336.7   626.8   356.1  629.94   365.8  632.01   375.6   634.8   385.3  638.42
     395  642.42     463  671.07   492.2  682.97   521.4  694.19   579.7  715.24
#Mann= 3 , 0 , 0
       0     .06       0   249.2    .045       0   278.3     .06       0
Bank Sta=249.2,278.3
XS Rating Curve= 0 ,0
Exp/Cntr=0.3,0.1

Type RM Length L Ch R = 1 ,676.6   ,448.8,478.1,504.2
XS GIS Cut Line= 4
     1464166.135       236141.57     1464075.683      236119.591
     1463712.402      236094.851     1463583.496      236123.497
#Sta/Elev= 30
       0  713.76    18.6  704.93    37.2  694.98    93.1  663.96   112.8  652.25
   122.6  648.36   132.4  645.83   142.3  642.61   152.1  638.36     162  633.06
   171.8   628.3   181.6  625.82   240.7  622.41   260.4  621.72   266.2 621.741
   270.2  621.76   280.1     623   286.2624.3564   289.9  625.18   299.8  626.66
   339.1  630.56     349  632.71   358.8  636.06     408  654.93   437.5  665.95
   457.2  673.01   476.1   679.4   485.5  682.89   532.7  701.64   589.3  725.02
#Mann= 3 , 0 , 0
       0     .06       0   266.2    .045       0   286.2     .06       0
Bank Sta=266.2,286.2
XS Rating Curve= 0 ,0
Exp/Cntr=0.3,0.1

Type RM Length L Ch R = 1 ,198.5   ,201.9,198.5,195.1
XS GIS Cut Line= 3
     1464212.576      236094.478     1464087.315      235847.889
     1463691.742      235774.382
#Sta/Elev= 30
       0  721.59     9.5  716.99    38.2  701.76    76.3  683.43   104.9  668.97
   143.1  646.92   152.6  641.99   162.1  638.19   171.7  636.05   190.7  633.68
   200.3  630.54   219.4  621.19   228.9  619.16   238.4  620.65     248  625.03
   257.5  629.29     267  630.72   276.6  631.19   296.2  630.85   325.6   631.2
   364.9   630.8   404.2  631.27   502.3  629.67   561.2  630.63     571  631.42
   580.8  632.74   610.2  638.57   659.3  649.27   669.1  650.83   678.9  651.62
#Mann= 3 , 0 , 0
       0     .06       0   219.4    .045       0     248     .06       0
Bank Sta=219.4,248
XS Rating Curve= 0 ,0
Exp/Cntr=0.3,0.1

Chan Stop Cuts=-1
Use User Specified Reach Order=0
Composite Channel Slope=5